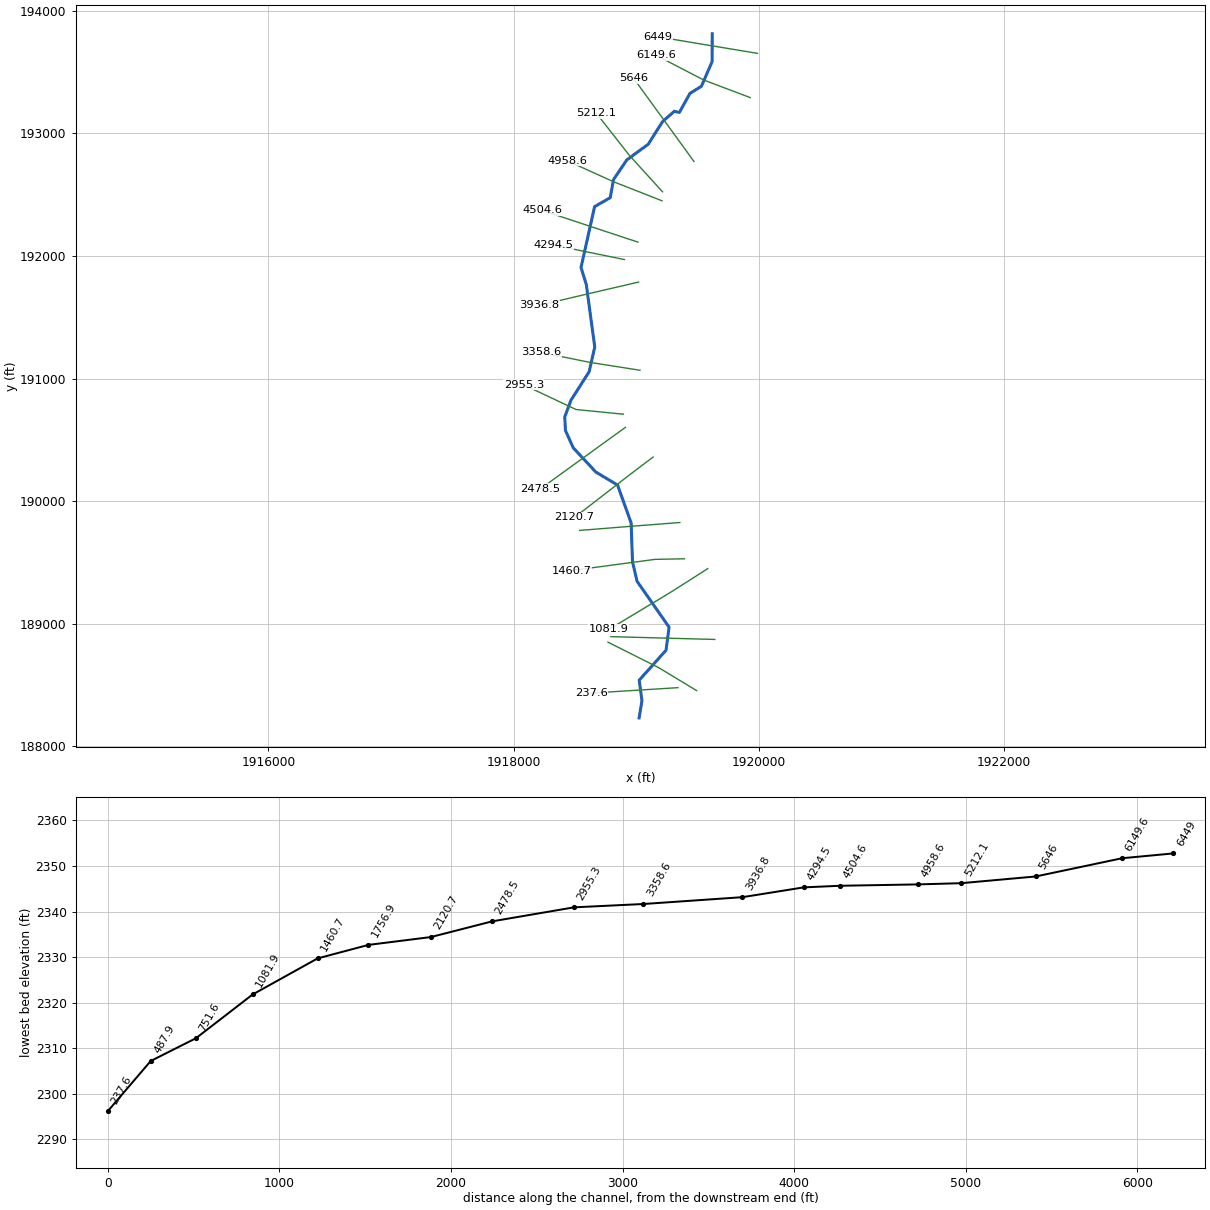
--- ClrkBrnch.prj (project) ---

Proj Title=ClrkBrnch
Current Plan=p01
Default Exp/Contr=0,0
English Units
Geom File=g01
Flow File=f01
Plan File=p01
BEGIN DESCRIPTION:
END DESCRIPTION:
DSS Export Rating Curves= 0
DSS Export Rating Curve Sorted= 0
DSS Export Volume Flow Curves= 0
DXF OffsetX= 0
DXF OffsetY= 0
DXF ScaleX= 0
DXF ScaleY= 0

--- ClrkBrnch.p01 (plan) ---

Plan Title=Floodplain
Program Version=4.00
Geom File=g01
Flow File=f01
K Sum by GR=0
Std Step Tol=0.01
Critical Tol=0.01
Num of Std Step Trials=20
Max Error Tol=0.3
Flow Tol Ratio=0.001
Split Flow NTrial=30
Split Flow Tol=0.02
Split Flow Ratio=0.02
Log Output Level=0
Friction Slope Method=1
Unsteady Friction Slope Method=2
Unsteady Bridges Friction Slope Method=1
Global Log Level=0
CheckData=False
Run HTab=0
Run UNet=0
Run PostProcess=0
UNET Theta=0
UNET Theta Warmup=0
UNET ZTol=0
UNET ZSATol=0
UNET MxIter=0
UNET MaxInSteps=0
UNET DtIC=0
UNET DtMin=0
UNET MaxCRTS=0
UNET WFStab=0
UNET SFStab=0
UNET WFX=0
UNET SFX=0
UNET DSS MLevel=0
UNET DZMax Abort=0
UNET Convert EG Bridges=0
UNET Use Existing IB Tables=0
UNET Froude Limit=0
UNET Froude Power=0
Write IC File=0
Echo Input=False
Echo Output=False
Write Detailed=0

--- ClrkBrnch.f01 (steady flow) ---

Flow Title=NFF Regression Equation
Program Version=4.00
Number of Profiles=1
Profile Names=P100yr
River Rch & RM=ClrkBrnch,Main      ,6449
492.1333
River Rch & RM=ClrkBrnch,Main      ,4504.6
602.2943
River Rch & RM=ClrkBrnch,Main      ,4504.6
537.6899
River Rch & RM=ClrkBrnch,Main      ,237.6
653.5281
Boundary for River Rch & Prof#=ClrkBrnch,Main      ,1
Up Type=0
Dn Type=3
Dn Slope=0.030498

--- ClrkBrnch.g01 (geometry) ---

Geom Title=USGS 3m DEM
Program Version=4.10

River Reach=ClrkBrnch       ,Main
Reach XY= 30
     1919618.904       193812.37     1919617.888       193584.94
     1919530.648       193384.42     1919436.898      193325.826
      1919350.96      193170.878     1919309.294      193179.993
     1919214.242      193096.659     1919097.054      192911.763
     1918921.273      192782.857       1918813.2      192621.399
     1918787.158      192475.565     1918659.554      192402.649
     1918548.877      191906.555     1918591.846      191767.232
     1918660.856      191258.117     1918614.781      191055.346
      1918466.44      190823.462      1918416.15      190687.517
     1918421.919      190577.418     1918485.671      190435.265
     1918670.159      190237.647     1918846.639      190132.379
     1918957.624      189822.944      1918968.62      189507.204
     1919005.703      189347.765     1919267.049      188973.106
     1919242.121      188784.987     1919023.599      188541.134
     1919045.736      188373.236      1919022.35      188232.897

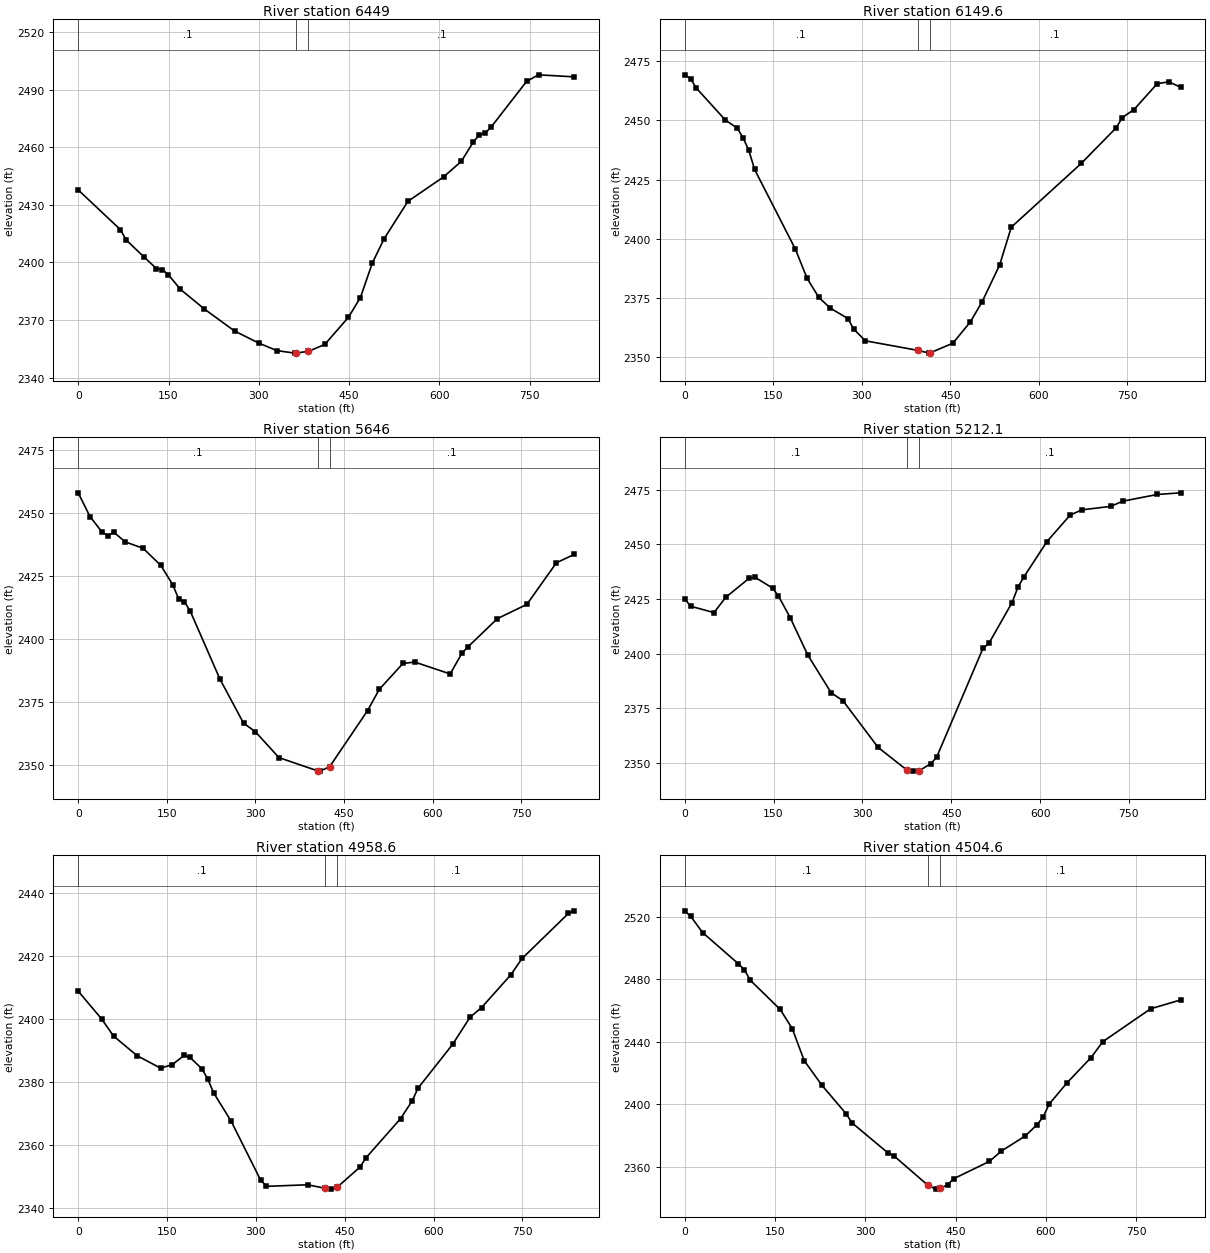
Type RM Length L Ch R = 1 ,6449    ,305.4,299.4,290.4
XS GIS Cut Line= 3
     1919987.688      193652.845     1919583.663       193719.55
      1919175.16      193787.789
#Sta/Elev= 30
       0 2437.81    69.9 2417.16    79.9 2411.65   109.9 2402.69   129.8 2396.84
   139.8 2396.31   149.8 2393.61   169.8 2385.98   209.7 2375.71   259.7 2364.28
   299.6 2358.04   329.6  2354.1   359.6 2352.76   362.3 2352.83   382.3 2353.68
   409.5 2357.28   448.9 2371.46   468.7 2381.73   488.4 2399.64   508.1 2412.38
   547.6 2431.86   606.7 2444.56   636.3  2452.7     656 2462.66   665.9 2466.43
   675.7 2467.33   685.6  2470.5   744.8 2494.39   764.5 2497.79   823.7 2496.74
#Mann= 3 , 0 , 0
       0      .1       0   362.3    .045       0   382.3      .1       0
Bank Sta=362.3,382.3
XS Rating Curve= 0 ,0
Exp/Cntr=0.3,0.1

Type RM Length L Ch R = 1 ,6149.6  ,517.5,503.3,487.4
XS GIS Cut Line= 3
     1919928.587      193291.977     1919549.786       193435.08
     1919163.483      193635.926
#Sta/Elev= 30
       0 2469.28     9.9 2467.66    19.8 2463.66    69.1 2450.13    88.9  2446.8
    98.8 2442.75   108.6 2437.41   118.5 2429.29   187.6 2395.61   207.4 2383.31
   227.2 2375.26   246.9 2370.68   276.5 2366.33   286.4 2361.86   306.2  2356.9
   394.9 2352.87   414.8  2351.7   414.9 2351.71   454.4  2355.9   484.1  2364.9
   503.9 2373.36   533.6 2388.91   553.4 2404.92   672.1 2431.89   731.5 2447.01
   741.4 2451.22   761.2 2454.58   800.7 2465.56   820.5 2466.33   840.3 2464.01
#Mann= 3 , 0 , 0
       0      .1       0   394.9    .045       0   414.9      .1       0
Bank Sta=394.9,414.9
XS Rating Curve= 0 ,0
Exp/Cntr=0.3,0.1

Type RM Length L Ch R = 1 ,5646    ,432,433.8,434.6
XS GIS Cut Line= 2
     1919469.924      192770.977     1918977.054      193450.288
#Sta/Elev= 30
       0 2458.13      20 2448.69      40 2442.67      50 2441.12      60  2442.5
    79.9 2438.64   109.9 2436.11   139.9  2429.3   159.9 2421.69   169.8 2416.19
   179.8 2414.92   189.8 2411.07   239.8 2384.23   279.8 2366.73   299.7 2363.36
   339.7 2353.07   405.6 2347.78   409.6  2347.7   425.6 2349.48   489.6 2371.69
   509.6 2380.17   549.5 2390.41   569.5 2390.98   629.5 2386.26   649.4  2394.5
   659.4 2396.97   709.4 2408.22   759.3 2413.86   809.3 2430.38   839.3 2433.68
#Mann= 3 , 0 , 0
       0      .1       0   405.6    .045       0   425.6      .1       0
Bank Sta=405.6,425.6
XS Rating Curve= 0 ,0
Exp/Cntr=0.3,0.1

Type RM Length L Ch R = 1 ,5212.1  ,242.2,253.6,264.1
XS GIS Cut Line= 3
     1919213.981      192523.162     1918941.139      192823.288
     1918675.116      193163.091
#Sta/Elev= 30
       0 2425.17     9.9 2421.74    49.5 2418.82    69.2 2425.78   108.8 2434.53
   118.7 2434.98   148.4 2430.06   158.3 2426.39   178.1 2416.52   207.8 2399.38
   247.3 2382.11   267.1  2378.5   326.5 2357.09   375.4 2346.67   385.8 2346.23
   395.4 2346.33   415.4 2349.64   425.2 2352.52   503.7 2402.54   513.5  2404.7
   552.7 2423.44   562.5  2430.4   572.3 2435.02   611.6 2451.36   650.8 2463.49
   670.4 2465.86   719.5 2467.47   739.1 2469.81   797.9 2472.91   837.2 2473.66
#Mann= 3 , 0 , 0
       0      .1       0   375.4    .045       0   395.4      .1       0
Bank Sta=375.4,395.4
XS Rating Curve= 0 ,0
Exp/Cntr=0.3,0.1

Type RM Length L Ch R = 1 ,4958.6  ,451.4,453.7,457.3
XS GIS Cut Line= 3
     1919209.479      192450.254     1918811.935      192606.531
     1918438.271      192775.836
#Sta/Elev= 30
       0 2408.92    39.7 2400.05    59.6 2394.66    99.3 2388.42   139.1 2384.44
   158.9 2385.56   178.8 2388.48   188.7 2387.86   208.6 2384.29   218.6 2381.06
   228.5 2376.64   258.3 2367.54     308 2348.84   317.9 2346.85   387.4 2347.34
   417.2 2346.23   427.2 2345.96   437.2 2346.56     476 2353.01   485.8  2355.9
   544.4  2368.4   563.9 2374.04   573.7 2378.05   632.3 2392.04   661.6 2400.63
   681.1 2403.72     730 2414.03   749.5 2419.32   827.6 2433.63   837.4 2434.48
#Mann= 3 , 0 , 0
       0      .1       0   417.2    .045       0   437.2      .1       0
Bank Sta=417.2,437.2
XS Rating Curve= 0 ,0
Exp/Cntr=0.3,0.1

Type RM Length L Ch R = 1 ,4504.6  ,207.2,210.2,213.1
XS GIS Cut Line= 2
     1919012.953      192113.217     1918230.718      192372.113
#Sta/Elev= 30
       0 2523.88     9.9  2520.4    29.8 2509.97    89.4 2489.91    99.3 2486.09
   109.2 2479.33   158.8  2460.7   178.7 2448.46   198.6 2427.95   228.3 2412.03
     268 2394.03     278  2388.1   337.5 2368.93   347.4 2367.05   404.1 2348.12
     417 2345.66   424.1 2346.13   436.8 2348.44   446.7 2352.27   506.3 2363.41
   526.2 2370.04   565.9 2379.72   585.7 2387.02   595.6 2391.89   605.6  2400.1
   635.4 2413.81   675.1  2429.9   694.9 2440.14   774.3 2461.18     824  2466.8
#Mann= 3 , 0 , 0
       0      .1       0   404.1    .045       0   424.1      .1       0
Bank Sta=404.1,424.1
XS Rating Curve= 0 ,0
Exp/Cntr=0.3,0.1

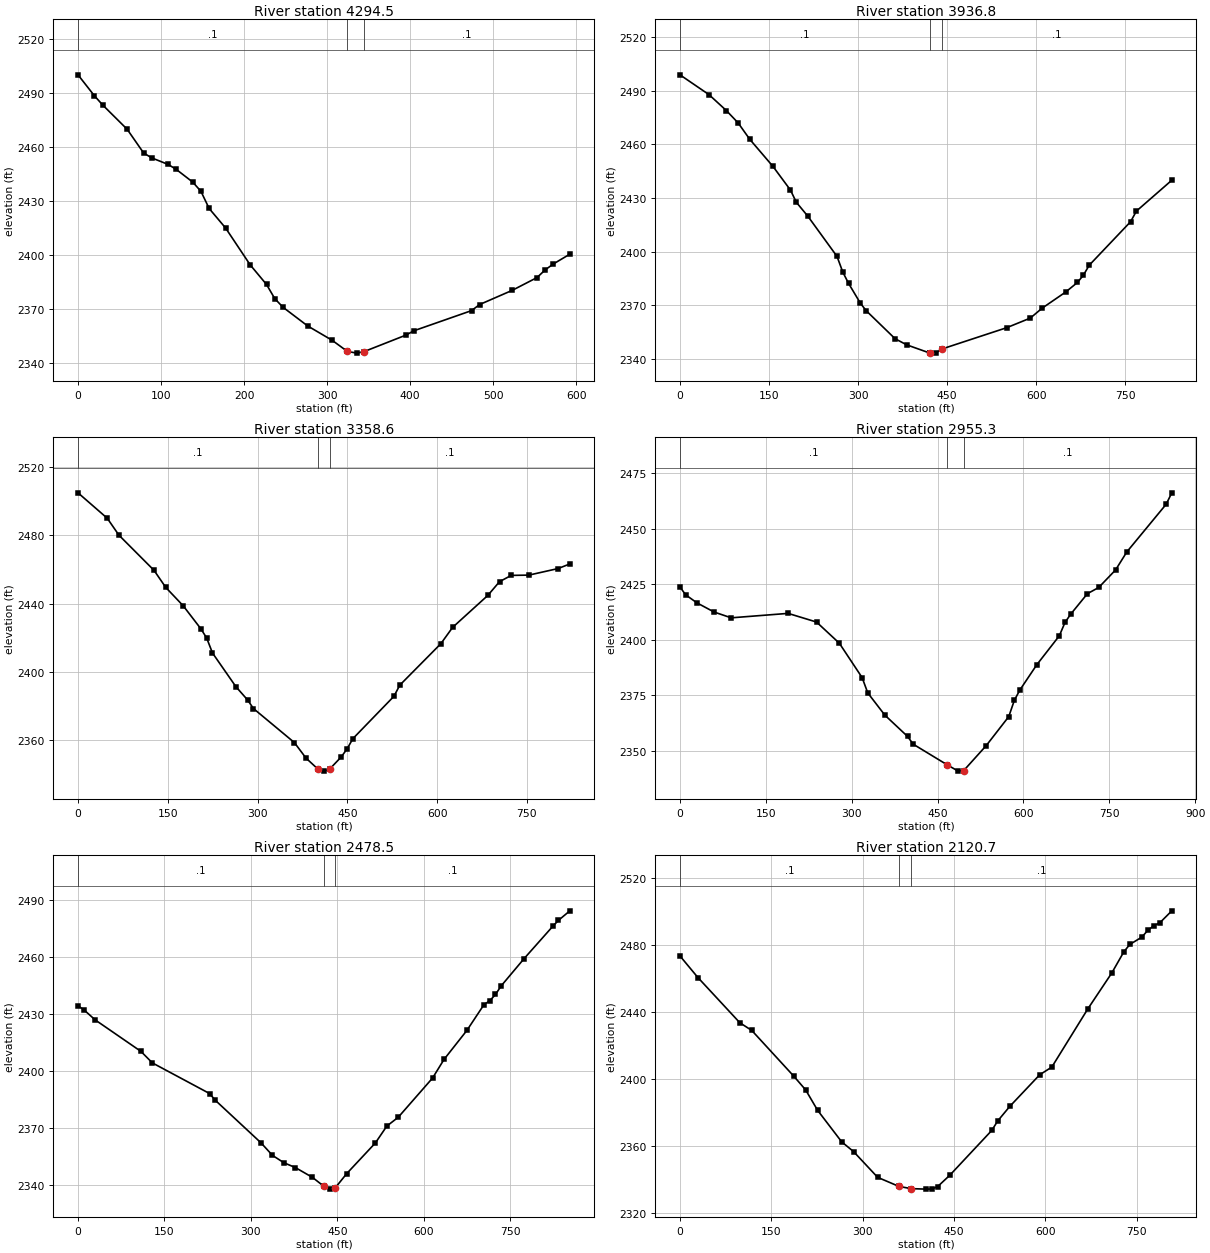
Type RM Length L Ch R = 1 ,4294.5  ,346.7,357.7,368.7
XS GIS Cut Line= 2
     1918903.203      191971.003     1918323.003      192089.673
#Sta/Elev= 30
       0 2499.97    19.7 2488.35    29.6 2483.26    59.2  2469.7      79 2456.54
    88.8  2453.8   108.6 2450.16   118.4 2447.38   138.2 2440.33     148 2435.23
   157.9 2425.69   177.7 2414.84   207.3 2394.36     227 2383.45   236.9 2375.61
   246.8 2370.81   276.4 2360.45     306 2352.44   324.2  2346.3   335.6 2345.31
   344.2 2346.12   394.8 2355.32   404.7 2357.78   473.8 2368.93   483.6 2372.32
   523.1 2380.26   552.7 2387.31   562.6 2391.62   572.5 2394.91   592.2 2400.31
#Mann= 3 , 0 , 0
       0      .1       0   324.2    .045       0   344.2      .1       0
Bank Sta=324.2,344.2
XS Rating Curve= 0 ,0
Exp/Cntr=0.3,0.1

Type RM Length L Ch R = 1 ,3936.8  ,589,578,565.9
XS GIS Cut Line= 3
     1919017.796      191787.333     1918607.375      191692.133
     1918210.945      191598.166
#Sta/Elev= 30
       0 2498.99      49 2487.87    78.4 2478.91      98 2472.06   117.6 2462.89
   156.8 2447.66   186.2 2434.44     196 2427.65   215.6 2419.76   264.6 2397.32
   274.4  2388.5   284.1  2382.2   303.7 2371.26   313.5    2367   362.5 2351.21
   382.1 2347.79   421.3 2343.16   421.4 2343.16   431.2 2343.27   441.4 2345.48
   550.5  2357.4   590.2 2362.76   610.1  2368.3   649.9 2377.37   669.7 2382.73
   679.7 2386.79   689.6  2392.4   759.2 2416.73   769.1  2422.7   828.7 2439.98
#Mann= 3 , 0 , 0
       0      .1       0   421.4    .045       0   441.4      .1       0
Bank Sta=421.4,441.4
XS Rating Curve= 0 ,0
Exp/Cntr=0.3,0.1

Type RM Length L Ch R = 1 ,3358.6  ,410.4,403.2,397.1
XS GIS Cut Line= 3
     1919030.032      191068.213     1918624.697      191132.075
     1918221.252      191213.139
#Sta/Elev= 30
       0 2504.94    48.8 2490.05    68.4 2480.09     127 2459.47   146.6 2449.46
   175.9 2438.61   205.2  2425.2   214.9 2419.82   224.7 2410.97   263.8 2391.21
   283.3 2383.44   293.1 2378.39   361.5 2358.42     381 2349.29   400.3 2343.04
   410.3 2341.66   420.3 2342.79   439.7 2349.95   449.5 2354.66   459.3 2360.72
   527.9 2385.58   537.7 2392.12   606.3 2416.44   625.9 2425.99   684.7 2444.74
   704.3 2452.82   723.9  2456.5   753.3 2456.66   802.2 2460.52   821.8 2463.22
#Mann= 3 , 0 , 0
       0      .1       0   400.3    .045       0   420.3      .1       0
Bank Sta=400.3,420.3
XS Rating Curve= 0 ,0
Exp/Cntr=0.3,0.1

Type RM Length L Ch R = 1 ,2955.3  ,449.9,476.6,503.3
XS GIS Cut Line= 3
     1918894.221      190709.967     1918508.362      190748.171
     1918081.837      190948.946
#Sta/Elev= 30
       0 2423.84     9.9 2420.31    29.8 2416.67    59.6 2412.56    89.5 2409.95
   188.9 2411.95   238.6 2408.05   278.4 2398.52   318.2 2383.04   328.1 2376.13
   357.9 2366.15   397.6 2356.55   407.4 2353.07   467.3 2343.69     486 2340.93
   495.8 2341.21   535.1 2352.45   574.4 2365.49   584.2 2372.87     594 2377.54
   623.4 2388.85   662.7 2401.86   672.6 2407.86   682.4 2411.54   711.8 2420.83
   731.5 2423.61     761 2431.52   780.6 2439.62   849.3 2461.08   859.2 2466.23
#Mann= 3 , 0 , 0
       0      .1       0   467.3    .045       0   495.8      .1       0
Bank Sta=467.3,495.8
XS Rating Curve= 0 ,0
Exp/Cntr=0.3,0.1

Type RM Length L Ch R = 1 ,2478.5  ,357,357.8,358.6
XS GIS Cut Line= 2
     1918910.825      190602.465     1918219.327      190102.554
#Sta/Elev= 30
       0 2434.44     9.9 2432.44    29.8 2427.04   109.1 2410.46     129 2404.38
   228.2 2388.24   238.1 2384.71   317.5 2362.25   337.3 2355.67   357.2 2351.76
     377 2349.24   406.8 2344.04   426.3  2339.4   436.6 2337.86   446.3 2338.56
   466.3 2346.08   515.9 2362.19   535.8 2371.09   555.6 2375.74   615.2 2396.43
     635 2406.21   674.7 2421.51   704.4 2435.12   714.4 2437.12   724.3 2440.45
   734.2 2444.98   773.9 2459.33   823.5  2476.3   833.4 2479.47   853.3 2484.52
#Mann= 3 , 0 , 0
       0      .1       0   426.3    .045       0   446.3      .1       0
Bank Sta=426.3,446.3
XS Rating Curve= 0 ,0
Exp/Cntr=0.3,0.1

Type RM Length L Ch R = 1 ,2120.7  ,378.7,363.8,349
XS GIS Cut Line= 3
       1919136.7      190360.173     1918971.762      190236.076
     1918496.041       189868.08
#Sta/Elev= 30
       0 2473.38    29.5  2460.5    98.3 2433.58     118 2428.96   186.8 2401.78
   206.4 2393.56   226.1 2381.36   265.6  2362.6   285.3 2356.72   324.7 2341.43
   359.9 2335.99   379.9 2334.71   403.6 2334.41   413.5 2334.45   423.3 2335.95
     443 2342.62   512.1 2369.39   521.9 2375.07   541.6 2383.68   590.9 2402.59
   610.7 2407.14   669.8  2441.8   709.2 2463.22     729 2475.83   738.8 2480.24
   758.6  2484.6   768.4 2488.66   778.3  2491.4   788.1 2493.14   807.8 2500.27
#Mann= 3 , 0 , 0
       0      .1       0   359.9    .045       0   379.9      .1       0
Bank Sta=359.9,379.9
XS Rating Curve= 0 ,0
Exp/Cntr=0.3,0.1

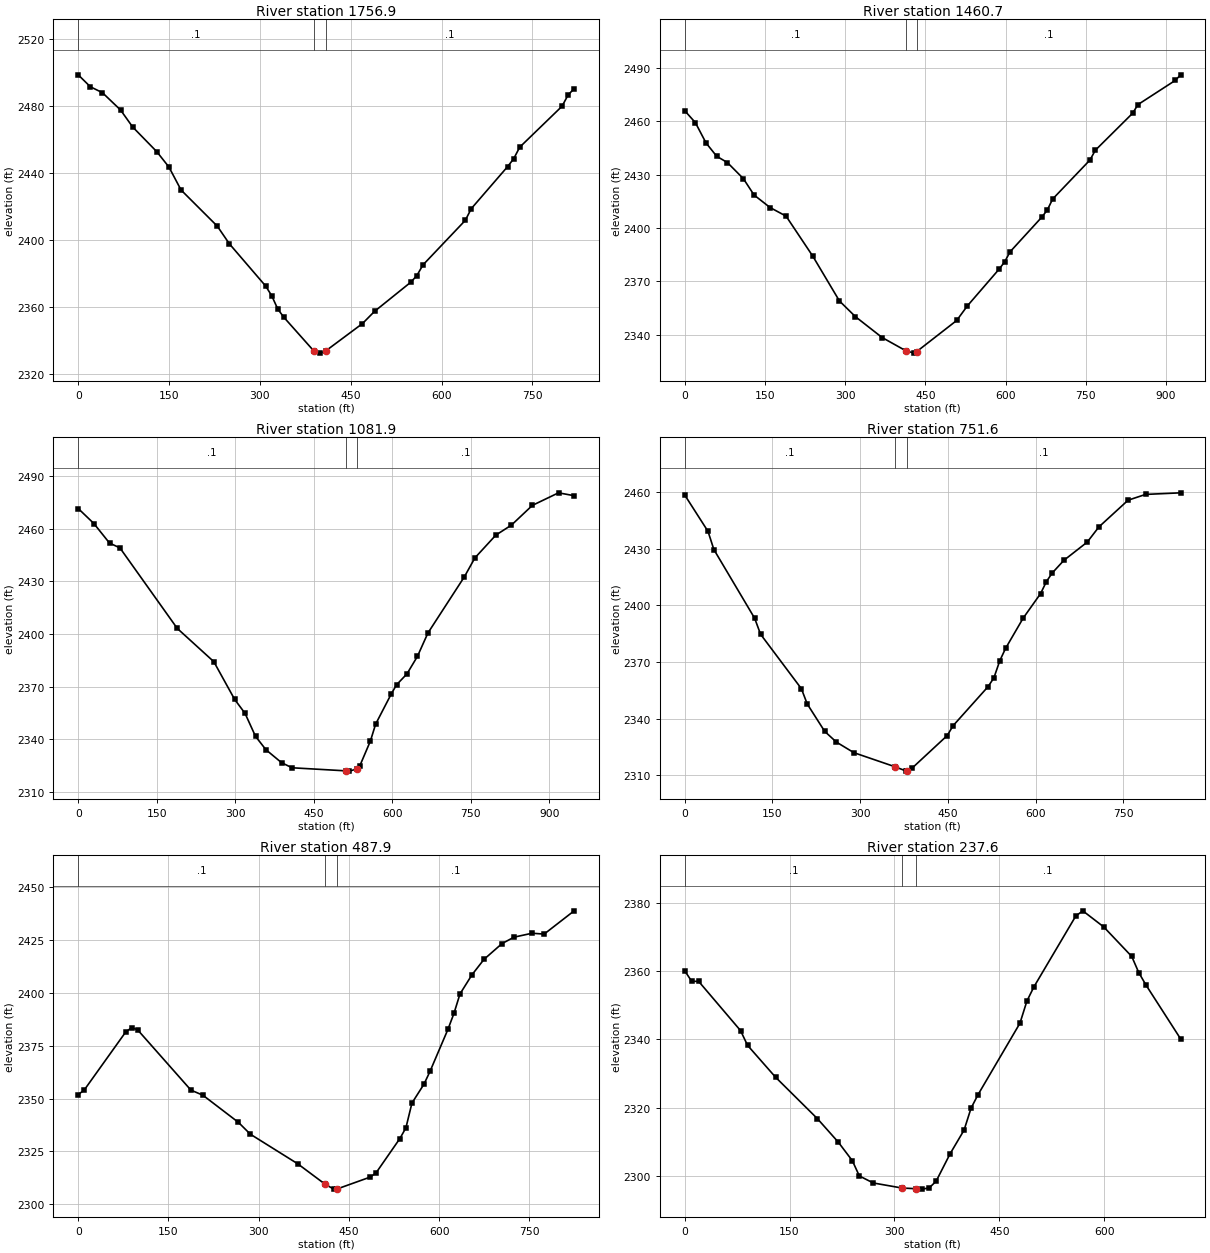
Type RM Length L Ch R = 1 ,1756.9  ,294.7,296.1,297.4
XS GIS Cut Line= 3
     1919354.816      189826.602     1918946.534      189795.047
     1918538.353      189762.182
#Sta/Elev= 30
       0 2498.65      20 2491.55      40 2487.99    69.9 2477.69    89.9 2467.56
   129.8  2452.8   149.8 2443.67   169.8 2429.98   229.7  2408.4   249.7 2397.85
   309.6 2372.67   319.6 2366.88   329.6 2358.95   339.6 2354.06   388.9 2334.06
   399.5 2332.69   408.9 2334.05   469.4 2350.31   489.4 2357.61   549.3 2375.01
   559.3 2378.96   569.3 2385.28   639.2 2411.85   649.2 2418.89   709.1 2443.91
   719.1 2448.58   729.1  2455.5     799 2479.92     809 2486.64     819 2490.41
#Mann= 3 , 0 , 0
       0      .1       0   388.9    .045       0   408.9      .1       0
Bank Sta=388.9,408.9
XS Rating Curve= 0 ,0
Exp/Cntr=0.3,0.1

Type RM Length L Ch R = 1 ,1460.7  ,368.6,378.9,389.1
XS GIS Cut Line= 3
     1919391.874      189530.736     1919152.409      189526.054
     1918470.662      189434.945
#Sta/Elev= 30
       0 2465.97      20 2459.24    39.9 2447.84    59.9 2440.32    79.8 2436.83
   109.8 2427.75   129.7 2418.58   159.7 2411.53   189.6  2406.7   239.5 2384.23
   289.4 2359.03   319.3 2350.21   369.1 2338.51   413.7 2331.03   428.9 2329.73
   433.7 2330.56   508.6 2348.08   528.6 2356.28   588.4 2377.09   598.4 2381.08
   608.3 2386.62   668.1 2406.26   678.1  2410.2   688.1 2416.34   757.9 2438.27
   767.8 2443.71   837.6 2464.52   847.6 2469.39   917.4 2482.98   927.3  2486.1
#Mann= 3 , 0 , 0
       0      .1       0   413.7    .045       0   433.7      .1       0
Bank Sta=413.7,433.7
XS Rating Curve= 0 ,0
Exp/Cntr=0.3,0.1

Type RM Length L Ch R = 1 ,1081.9  ,344.4,330.2,316
XS GIS Cut Line= 3
      1919582.82      189450.653     1919271.793      189252.727
     1918775.395      188954.585
#Sta/Elev= 30
       0  2471.4    29.9 2462.85    59.8 2451.72    79.7 2448.97   189.3 2403.09
   259.1 2384.16   298.9 2362.68   318.8 2354.71   338.8 2341.63   358.7 2334.01
   388.6 2326.62   408.6 2323.72   511.9 2321.96   518.4 2321.81   531.9 2323.02
   538.4 2325.01   558.4 2339.01   568.3 2348.54   598.3 2365.83   608.3 2370.99
   628.2 2377.21   648.2 2387.16   668.2 2400.45   738.1 2432.59     758 2443.25
     798 2456.23   827.9 2461.96   867.8 2473.17   917.8 2480.33   947.7  2478.7
#Mann= 3 , 0 , 0
       0      .1       0   511.9    .045       0   531.9      .1       0
Bank Sta=511.9,531.9
XS Rating Curve= 0 ,0
Exp/Cntr=0.3,0.1

Type RM Length L Ch R = 1 ,751.6   ,274.2,263.7,253.2
XS GIS Cut Line= 2
     1919640.017      188872.956     1918792.444      188895.967
#Sta/Elev= 30
       0 2458.39    39.9 2439.09    49.9  2429.5   119.7 2393.08   129.7 2384.68
   199.5 2355.86   209.5 2347.78   239.4 2333.25   259.4 2327.59   289.3 2321.98
   360.1 2314.48     379 2312.22   380.1  2312.4     389 2313.86   448.9 2331.06
   458.9 2336.26   518.7 2356.93   528.7  2361.6   538.7 2370.62   548.6 2377.16
   578.6 2393.14   608.5 2406.18   618.5 2412.56   628.4 2417.08   648.4  2423.8
   688.3 2433.44   708.2 2441.46   758.1  2455.6     788 2458.66   847.9  2459.5
#Mann= 3 , 0 , 0
       0      .1       0   360.1    .045       0   380.1      .1       0
Bank Sta=360.1,380.1
XS Rating Curve= 0 ,0
Exp/Cntr=0.3,0.1

Type RM Length L Ch R = 1 ,487.9   ,236.9,250.3,263.7
XS GIS Cut Line= 3
     1919491.491      188456.027     1919179.113       188644.81
     1918768.317      188850.767
#Sta/Elev= 30
       0 2351.87     9.9 2353.97    78.9 2381.39    88.8 2383.48    98.6 2382.48
   187.4 2353.96   207.2 2351.58   266.4 2338.73   286.1 2333.17     365 2319.17
   410.6 2309.51   424.9 2307.22   430.6 2307.32   484.9 2312.85   494.9 2314.79
   534.8 2331.12   544.8 2336.16   554.8 2347.84   574.8 2356.76   584.8 2362.77
   614.7 2382.69   624.7 2390.22   634.7 2399.38   654.7 2408.45   674.7 2415.73
   704.6 2423.16   724.6 2426.19   754.6 2428.04   774.6 2427.63   824.5 2438.62
#Mann= 3 , 0 , 0
       0      .1       0   410.6    .045       0   430.6      .1       0
Bank Sta=410.6,430.6
XS Rating Curve= 0 ,0
Exp/Cntr=0.3,0.1

Type RM Length L Ch R = 1 ,237.6   ,236.6,237.5,238.5
XS GIS Cut Line= 2
     1919339.339      188479.871     1918631.424      188435.464
#Sta/Elev= 30
       0  2360.1      10 2357.01      20 2356.98    79.9 2342.58    89.9 2338.27
   129.9 2328.96   189.8 2316.82   219.8 2309.92   239.8 2304.51   249.8 2300.06
   269.7    2298   310.6 2296.53   330.6 2296.32   339.7  2296.2   349.7 2296.56
   359.6 2298.51   379.6 2306.54   399.6 2313.48   409.6  2319.9   419.6 2323.85
   479.5 2344.74   489.5 2351.25   499.5 2355.38   559.4 2376.11   569.4 2377.62
   599.4  2372.9   639.4 2364.27   649.4 2359.57   659.4 2356.03   709.3 2340.15
#Mann= 3 , 0 , 0
       0      .1       0   310.6    .045       0   330.6      .1       0
Bank Sta=310.6,330.6
XS Rating Curve= 0 ,0
Exp/Cntr=0.3,0.1

Chan Stop Cuts=-1
Use User Specified Reach Order=0
Composite Channel Slope=5